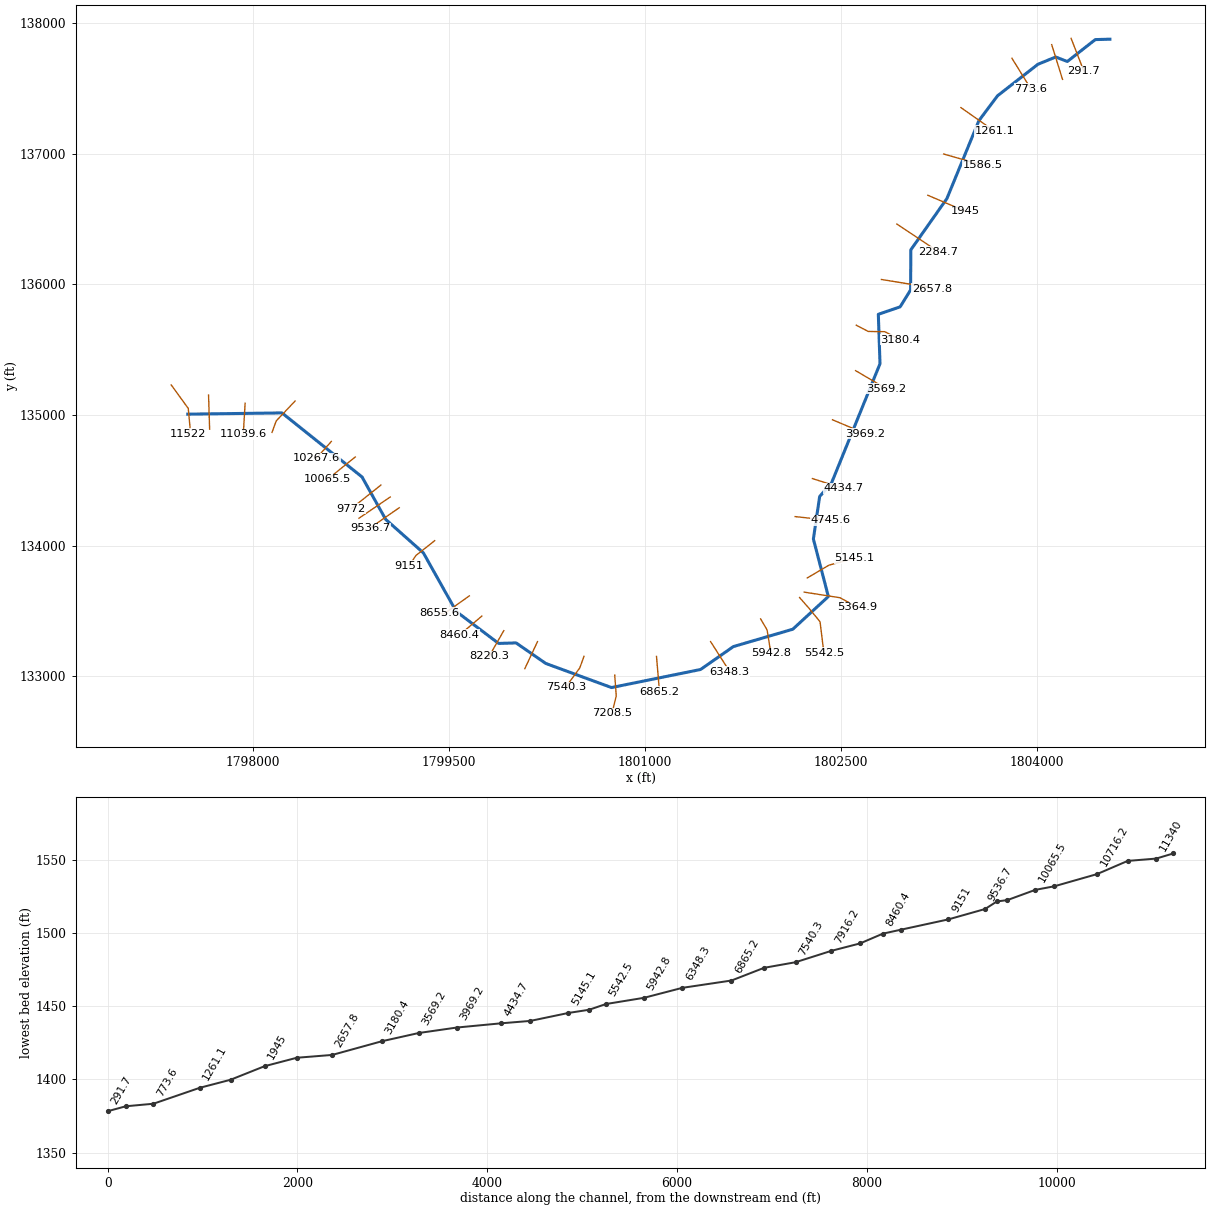
--- Mill Creek B.prj (project) ---

Proj Title=Mill Creek B
Current Plan=p01
Default Exp/Contr=0,0
English Units
Geom File=g01
Flow File=f01
Plan File=p01
BEGIN DESCRIPTION:
END DESCRIPTION:
DSS Export Rating Curves= 0
DSS Export Rating Curve Sorted= 0
DSS Export Volume Flow Curves= 0
DXF OffsetX= 0
DXF OffsetY= 0
DXF ScaleX= 0
DXF ScaleY= 0

--- Mill Creek B.p01 (plan) ---

Plan Title=Floodplain
Program Version=4.00
Geom File=g01
Flow File=f01
K Sum by GR=0
Std Step Tol=0.01
Critical Tol=0.01
Num of Std Step Trials=20
Max Error Tol=0.3
Flow Tol Ratio=0.001
Split Flow NTrial=30
Split Flow Tol=0.02
Split Flow Ratio=0.02
Log Output Level=0
Friction Slope Method=1
Unsteady Friction Slope Method=2
Unsteady Bridges Friction Slope Method=1
Global Log Level=0
CheckData=False
Run HTab=0
Run UNet=0
Run PostProcess=0
UNET Theta=0
UNET Theta Warmup=0
UNET ZTol=0
UNET ZSATol=0
UNET MxIter=0
UNET MaxInSteps=0
UNET DtIC=0
UNET DtMin=0
UNET MaxCRTS=0
UNET WFStab=0
UNET SFStab=0
UNET WFX=0
UNET SFX=0
UNET DSS MLevel=0
UNET DZMax Abort=0
UNET Convert EG Bridges=0
UNET Use Existing IB Tables=0
UNET Froude Limit=0
UNET Froude Power=0
Write IC File=0
Echo Input=False
Echo Output=False
Write Detailed=0

--- Mill Creek B.f01 (steady flow) ---

Flow Title=NFF Regression Equation
Program Version=4.00
Number of Profiles=1
Profile Names=P100yr
River Rch & RM=Mill Creek B,Main      ,11522
621.6324
River Rch & RM=Mill Creek B,Main      ,11340
645.8979
River Rch & RM=Mill Creek B,Main      ,10716.2
700.5028
River Rch & RM=Mill Creek B,Main      ,8655.6
754.2554
River Rch & RM=Mill Creek B,Main      ,6865.2
824.6971
River Rch & RM=Mill Creek B,Main      ,6865.2
1191.741
River Rch & RM=Mill Creek B,Main      ,5942.8
1267.256
River Rch & RM=Mill Creek B,Main      ,291.7
1401.266
Boundary for River Rch & Prof#=Mill Creek B,Main      ,1
Up Type=0
Dn Type=3
Dn Slope=0.015301

--- Mill Creek B.g01 (geometry) ---

Geom Title=Geometry
Program Version=4.00

River Reach=Mill Creek B    ,Main
Reach XY= 30
     1797504.069      135006.212     1798224.909      135015.667
     1798837.704      134525.511     1799018.055      134201.385
      1799306.73      133944.916     1799558.129      133496.676
     1799882.466      133251.986     1800016.105      133255.978
     1800242.815       133098.99     1800746.179       132914.33
     1801427.624      133052.589     1801678.805      133227.963
     1802133.021      133360.612     1802405.334      133610.697
     1802290.756       134051.21     1802338.761      134376.384
     1802429.297      134478.682     1802800.588      135392.161
     1802787.683      135770.074     1802954.519      135827.222
     1803034.566      135956.641     1803036.462      136263.533
     1803312.471      136656.069     1803556.928      137251.238
     1803699.775      137442.083     1804008.789      137683.176
      1804144.63      137738.653     1804233.808      137704.434
     1804447.422      137871.903     1804559.227      137875.136

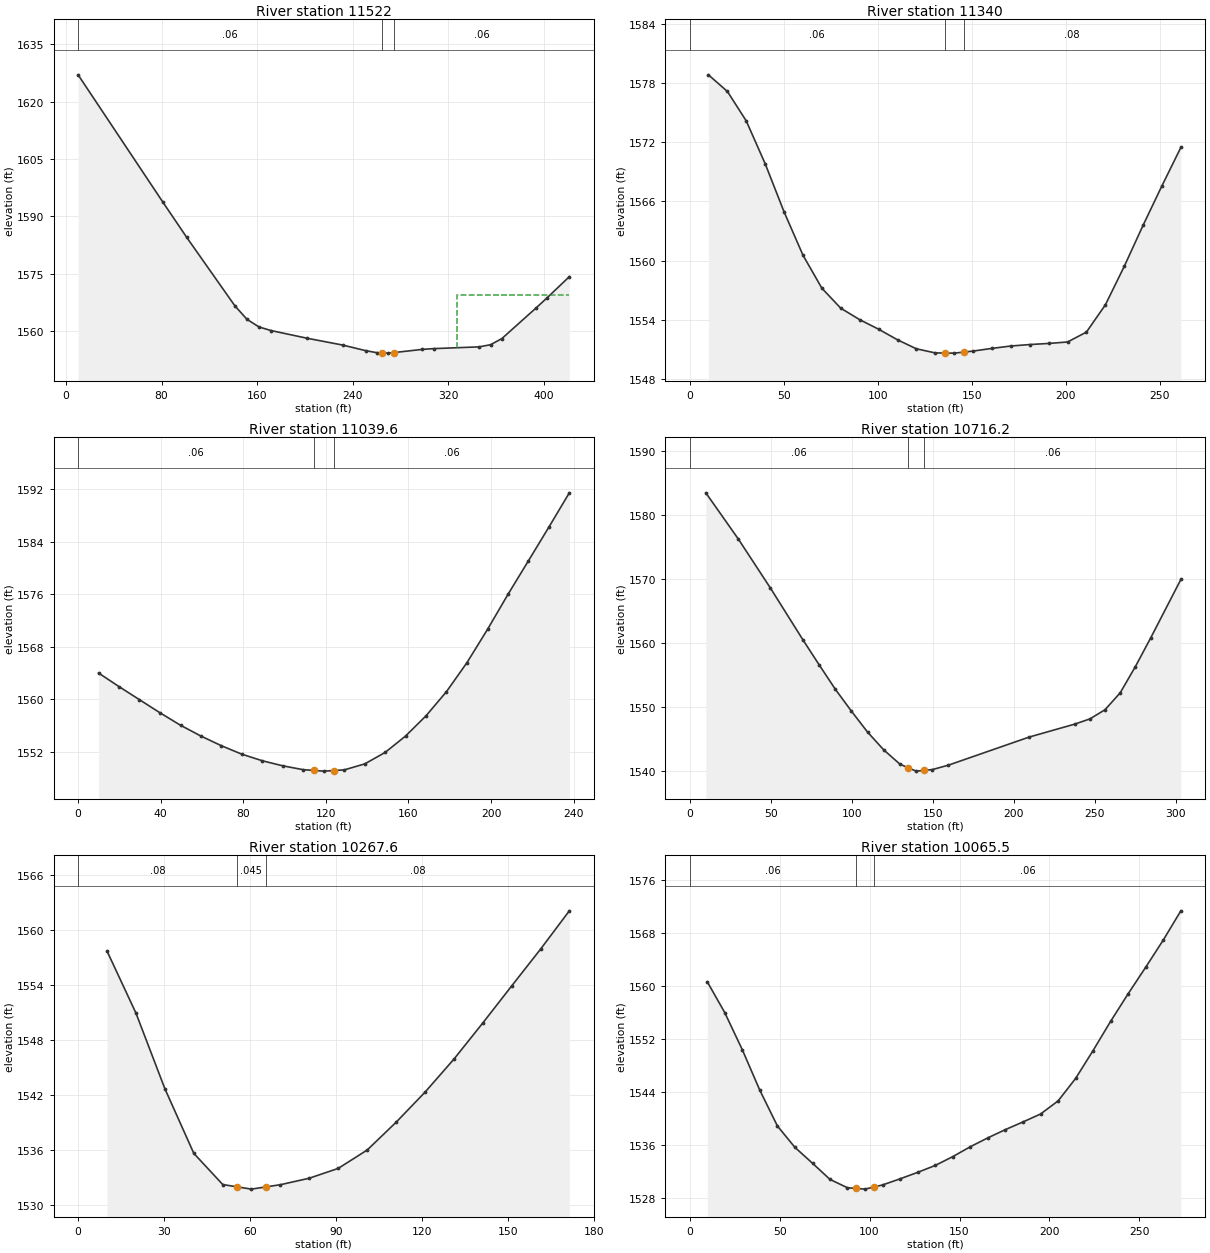
Type RM Length L Ch R = 1 ,11522   ,184.2,182,195
XS GIS Cut Line= 4
      1797377.47      135229.914     1797507.968      135050.038
     1797522.076      134898.377     1797504.441      134854.878
#Sta/Elev= 22
    10.1 1627.02    80.8 1593.83     101 1584.49   141.4 1566.54   151.5 1563.02
   161.6 1561.01   171.7 1560.07     202 1558.05   231.7 1556.27   250.8 1554.82
   260.3 1554.27   264.8 1554.22   269.8 1554.16   274.8 1554.31   298.4 1555.14
   307.9 1555.34     346  1555.8   355.5 1556.36     365 1557.97   393.3 1565.89
   402.7 1568.59   421.5 1574.18
#Mann= 3 , 0 , 0
    10.1     .06       0   264.8    .045       0   274.8     .06       0
#XS Ineff= 2 , 0
                          327.18         1569.48
Permanent Ineff=
       F       F
Bank Sta=264.8,274.8
XS Rating Curve= 0 ,0
Exp/Cntr=0.3,0.1

Type RM Length L Ch R = 1 ,11340   ,300.1,300.4,280.6
XS GIS Cut Line= 2
     1797663.156       135152.32     1797671.385      134891.324
#Sta/Elev= 28
      10 1578.84    20.1 1577.15    30.1 1574.17    40.2 1569.81    50.2 1564.95
    60.3 1560.54    70.3 1557.21    80.3 1555.19    90.4 1554.02   100.4 1553.06
   110.5 1551.98   120.5 1551.07   130.6 1550.65   135.6 1550.64   140.6 1550.63
   145.6 1550.73   150.7 1550.84   160.7 1551.11   170.7 1551.35   180.8  1551.5
   190.8 1551.61   200.9 1551.76   210.9 1552.76     221 1555.53     231 1559.42
     241 1563.58   251.1 1567.61   261.1 1571.48
#Mann= 3 , 0 , 0
       0     .06       0   135.6    .045       0   145.6     .08       0
Bank Sta=135.6,145.6
XS Rating Curve= 0 ,0
Exp/Cntr=0.3,0.1

Type RM Length L Ch R = 1 ,11039.6 ,337.7,323.4,309.3
XS GIS Cut Line= 2
     1797942.963       135090.01     1797928.855      134852.527
#Sta/Elev= 26
     9.9 1563.99    19.8 1561.92    29.7 1559.93    39.7 1557.92    49.6 1556.03
    59.5 1554.38    69.4 1552.91    79.3 1551.62    89.2 1550.62    99.1 1549.85
     109 1549.26     114 1549.15     119 1549.04     124 1549.13   128.9 1549.23
   138.8 1550.14   148.7 1551.89   158.6 1554.39   168.5 1557.47   178.4 1561.15
   188.3 1565.56   198.3 1570.65   208.2 1575.98   218.1 1581.09     228 1586.22
   237.9 1591.44
#Mann= 3 , 0 , 0
       0     .06       0     114    .045       0     124     .06       0
Bank Sta=114,124
XS Rating Curve= 0 ,0
Exp/Cntr=0.3,0.1

Type RM Length L Ch R = 1 ,10716.2 ,446.6,448.6,450.1
XS GIS Cut Line= 3
     1798325.053      135106.469     1798180.839      134954.298
     1798148.584      134866.525
#Sta/Elev= 23
      10 1583.49      30  1576.3    49.9 1568.61    69.9 1560.55    79.9 1556.65
    89.9 1552.83    99.8 1549.42   109.8 1546.14   119.8 1543.35   129.8 1541.12
   134.8 1540.57   139.8 1540.03   144.8 1540.15   149.8 1540.27   159.7 1540.96
   209.7 1545.36   237.7 1547.37   247.1 1548.19   256.4 1549.62   265.8 1552.27
   275.1 1556.34   284.5 1560.79   303.2 1569.96
#Mann= 3 , 0 , 0
       0     .06       0   134.8    .045       0   144.8     .06       0
Bank Sta=134.8,144.8
XS Rating Curve= 0 ,0
Exp/Cntr=0.3,0.1

Type RM Length L Ch R = 1 ,10267.6 ,205.4,202.1,198.8
XS GIS Cut Line= 2
     1798602.509      134797.271      1798488.47      134669.123
#Sta/Elev= 19
    10.1 1557.72    20.2 1550.95    30.3  1542.7    40.4 1535.65    50.5 1532.25
    55.5    1532    60.5 1531.75    65.5 1531.99    70.6 1532.23    80.7 1532.94
    90.8 1534.01   100.9 1536.01     111 1539.04   121.1 1542.32   131.2 1545.93
   141.3 1549.88   151.4 1553.93   161.5 1557.95   171.5 1562.11
#Mann= 3 , 0 , 0
       0     .08       0    55.5    .045       0    65.5     .08       0
Bank Sta=55.5,65.5
XS Rating Curve= 0 ,0
Exp/Cntr=0.3,0.1

Type RM Length L Ch R = 1 ,10065.5 ,293.6,293.5,293.4
XS GIS Cut Line= 3
     1798785.854      134678.713       1798679.6      134593.025
     1798573.347      134507.337
#Sta/Elev= 30
     9.8 1560.63    19.5 1555.98    29.3 1550.34      39 1544.24    48.8 1538.82
    58.5  1535.6    68.3 1533.19      78 1530.75    87.7 1529.49    92.5 1529.39
    97.5 1529.28   102.5 1529.61   107.2 1529.91     117 1530.84   126.7 1531.81
   136.5 1532.86   146.3  1534.2     156 1535.69   165.8 1537.04   175.5 1538.28
   185.3 1539.44     195 1540.63   204.8 1542.62   214.5 1546.01   224.2 1550.22
     234 1554.66   243.7 1558.81   253.5 1562.84   263.2 1566.92     273 1571.35
#Mann= 3 , 0 , 0
       0     .06       0    92.5    .045       0   102.5     .06       0
Bank Sta=92.5,102.5
XS Rating Curve= 0 ,0
Exp/Cntr=0.3,0.1

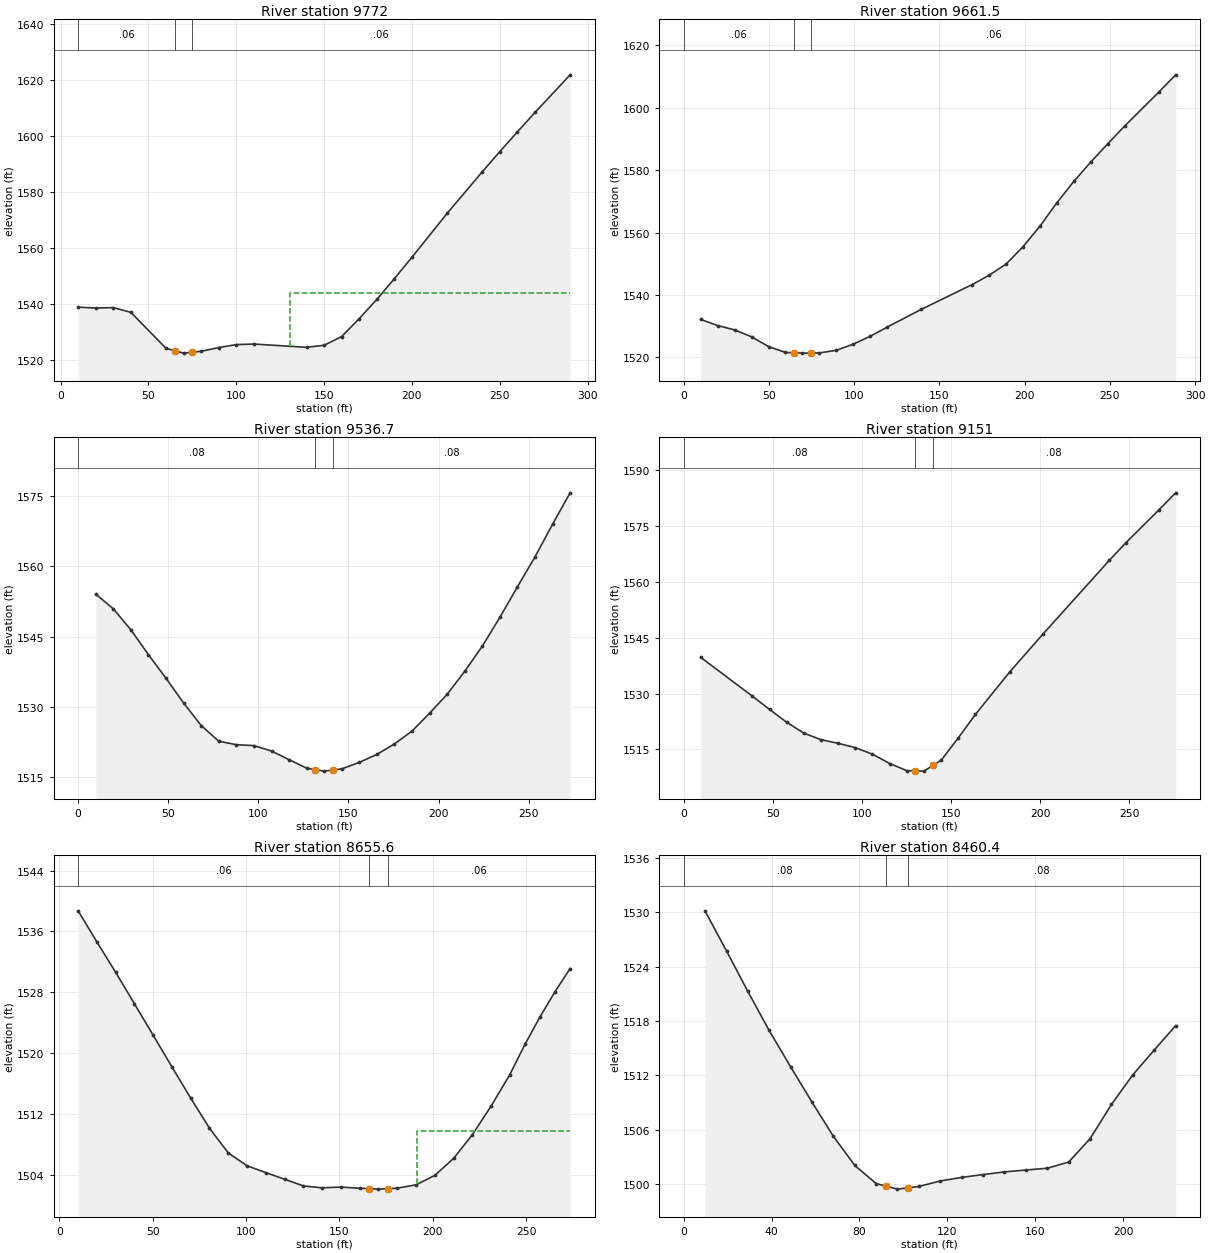
Type RM Length L Ch R = 1 ,9772    ,111.9,110.4,108.9
XS GIS Cut Line= 2
     1798981.834      134463.869     1798755.032      134283.085
#Sta/Elev= 25
      10 1538.78      20 1538.46      30 1538.62      40 1536.93      60 1524.04
      65 1523.18      70 1522.32      75 1522.64      80 1522.97      90 1524.31
     100 1525.37     110 1525.57     140 1524.41     150 1525.13     160 1528.26
     170 1534.69     180 1541.56     190 1549.02     200 1556.67     220 1572.36
     240 1587.25     250 1594.48     260 1601.55     270 1608.49     290 1621.97
#Mann= 3 , 0 , 0
      10     .06       0      65    .045       0      75     .06       0
#XS Ineff= 2 , 0
                          130.37         1543.91
Permanent Ineff=
       F       F
Bank Sta=65,75
XS Rating Curve= 0 ,0
Exp/Cntr=0.3,0.1

Type RM Length L Ch R = 1 ,9661.5  ,124.7,124.8,125.1
XS GIS Cut Line= 2
     1799053.081      134372.341     1798814.422        134210.1
#Sta/Elev= 27
      10 1532.18    19.9 1530.23    29.9 1528.82    39.8 1526.63    49.8 1523.49
    59.7 1521.61    64.7  1521.5    69.7 1521.39    74.7 1521.43    79.6 1521.46
    89.6  1522.3    99.5 1524.27   109.5  1526.8   119.4 1529.72   139.3 1535.39
   169.2 1543.33   179.1 1546.32   189.1  1549.9     199 1555.44     209 1562.05
   218.9 1569.53   228.9  1576.4   238.8 1582.58   248.8 1588.45   258.7 1594.12
   278.6 1604.91   288.6 1610.51
#Mann= 3 , 0 , 0
       0     .06       0    64.7    .045       0    74.7     .06       0
Bank Sta=64.7,74.7
XS Rating Curve= 0 ,0
Exp/Cntr=0.3,0.1

Type RM Length L Ch R = 1 ,9536.7  ,384.5,385.8,386.9
XS GIS Cut Line= 3
     1799122.392       134290.36     1799010.123      134212.716
     1798898.298      134134.439
#Sta/Elev= 30
     9.8 1554.04    19.5 1550.94    29.3 1546.41      39 1541.13    48.8 1536.06
    58.5 1530.81    68.3 1525.97      78 1522.64    87.8 1521.87    97.5 1521.69
   107.3 1520.52     117 1518.69   126.8 1516.87   131.5 1516.56   136.5 1516.23
   141.5 1516.48   146.3 1516.72     156 1518.09   165.8 1519.82   175.5 1522.03
   185.3  1524.8     195  1528.6   204.8 1532.67   214.5 1537.56   224.3 1542.95
     234  1549.1   243.8 1555.65   253.5 1562.02   263.3 1569.03     273 1575.72
#Mann= 3 , 0 , 0
       0     .08       0   131.5    .045       0   141.5     .08       0
Bank Sta=131.5,141.5
XS Rating Curve= 0 ,0
Exp/Cntr=0.3,0.1

Type RM Length L Ch R = 1 ,9151    ,496.4,495.4,494.4
XS GIS Cut Line= 3
     1799393.413      134038.104     1799249.724      133924.804
     1799197.895      133847.569
#Sta/Elev= 23
     9.6  1539.7    38.5 1529.31    48.2 1525.72    57.8 1522.28    67.4 1519.37
      77 1517.62    86.7 1516.63    96.3 1515.47   105.9 1513.71   115.6 1511.21
   125.2 1509.29   129.8 1509.24   134.8 1509.17   139.8 1510.69   144.5 1512.11
   154.1 1518.12   163.7 1524.42     183 1535.85   201.6 1545.99   238.8 1565.77
   248.1  1570.5   266.7 1579.35     276 1583.89
#Mann= 3 , 0 , 0
       0     .08       0   129.8    .045       0   139.8     .08       0
Bank Sta=129.8,139.8
XS Rating Curve= 0 ,0
Exp/Cntr=0.3,0.1

Type RM Length L Ch R = 1 ,8655.6  ,193.3,195.1,196.9
XS GIS Cut Line= 3
     1799658.398      133615.795     1799461.734       133476.13
     1799430.508      133484.348
#Sta/Elev= 30
    10.1 1538.71    20.1 1534.65    30.2 1530.64    40.2 1526.53    50.3 1522.38
    60.3 1518.24    70.4 1514.13    80.4  1510.2    90.5 1506.94   100.5 1505.27
   110.6 1504.36   120.6  1503.5   130.7 1502.62   140.7 1502.37   150.8 1502.47
   160.8 1502.31   165.9 1502.26   170.9  1502.2   175.9 1502.26   180.9 1502.32
     191 1502.77     201 1503.99   211.1 1506.23   221.1 1509.32   231.2  1513.1
   241.2 1517.21   249.3 1521.18   257.4 1524.81   265.4  1528.1   273.5 1531.14
#Mann= 3 , 0 , 0
    10.1     .06       0   165.9    .045       0   175.9     .06       0
#XS Ineff= 2 , 0
                          191.78         1509.89
Permanent Ineff=
       F       F
Bank Sta=165.9,175.9
XS Rating Curve= 0 ,0
Exp/Cntr=0.3,0.1

Type RM Length L Ch R = 1 ,8460.4  ,232.9,240.1,247.4
XS GIS Cut Line= 2
     1799754.276      133461.339     1799583.352      133316.712
#Sta/Elev= 25
     9.7 1530.17    19.5 1525.74    29.2 1521.27    38.9 1516.96    48.7 1512.93
    58.4 1509.05    68.1 1505.28    77.9 1502.05    87.6 1500.05    92.3 1499.76
    97.3 1499.44   102.3 1499.59   107.1 1499.74   116.8 1500.34   126.6 1500.74
   136.3 1501.05     146 1501.34   155.8 1501.55   165.5 1501.75   175.2 1502.43
     185 1505.02   194.7  1508.8   204.4 1512.06   214.2 1514.81   223.9 1517.49
#Mann= 3 , 0 , 0
       0     .08       0    92.3    .045       0   102.3     .08       0
Bank Sta=92.3,102.3
XS Rating Curve= 0 ,0
Exp/Cntr=0.3,0.1

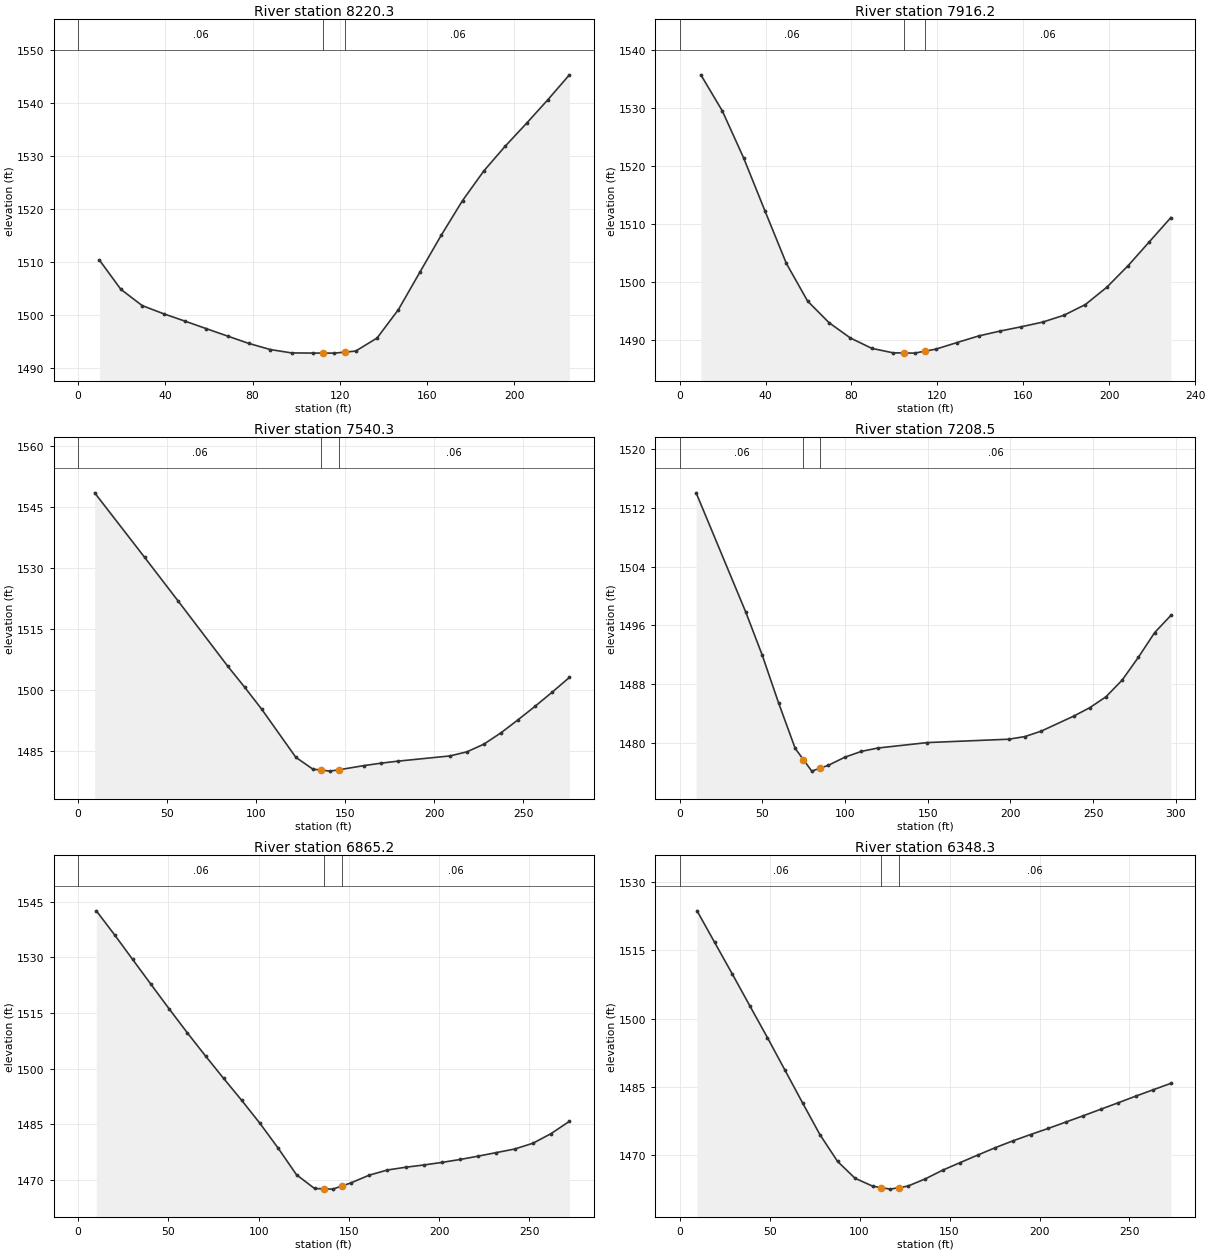
Type RM Length L Ch R = 1 ,8220.3  ,302.5,304.1,305.6
XS GIS Cut Line= 2
     1799921.912      133349.582     1799810.154      133154.006
#Sta/Elev= 25
     9.8 1510.33    19.6 1504.82    29.4 1501.75    39.2 1500.21      49 1498.82
    58.8  1497.4    68.6 1495.99    78.3 1494.61    88.1 1493.46    97.9 1492.82
   107.7 1492.79   112.5 1492.79   117.5 1492.78   122.5 1492.98   127.3 1493.17
   137.1 1495.63   146.9    1501   156.7 1508.04   166.5 1515.01   176.3 1521.58
   186.1 1527.19   195.9 1531.85   205.7 1536.18   215.5 1540.64   225.3  1545.3
#Mann= 3 , 0 , 0
       0     .06       0   112.5    .045       0   122.5     .06       0
Bank Sta=112.5,122.5
XS Rating Curve= 0 ,0
Exp/Cntr=0.3,0.1

Type RM Length L Ch R = 1 ,7916.2  ,379.9,376,372
XS GIS Cut Line= 2
      1800179.94      133265.763     1800082.974      133058.683
#Sta/Elev= 25
     9.9 1535.68    19.9 1529.45    29.8 1521.36    39.8 1512.16    49.7 1503.16
    59.6 1496.66    69.6 1492.93    79.5  1490.3    89.5 1488.51    99.4 1487.74
   104.4 1487.72   109.4 1487.69   114.4 1488.04   119.3 1488.38   129.2 1489.52
   139.2 1490.65   149.1 1491.49   159.1 1492.24     169 1493.04   178.9 1494.22
   188.9 1496.07   198.8 1499.03   208.8 1502.78   218.7  1506.9   228.7 1511.07
#Mann= 3 , 0 , 0
       0     .06       0   104.4    .045       0   114.4     .06       0
Bank Sta=104.4,114.4
XS Rating Curve= 0 ,0
Exp/Cntr=0.3,0.1

Type RM Length L Ch R = 1 ,7540.3  ,317.6,331.8,346
XS GIS Cut Line= 3
      1800535.56      133153.138     1800503.708      133065.257
     1800396.111      132917.815
#Sta/Elev= 22
     9.3 1548.54    37.4 1532.62    56.1 1521.93    84.1 1505.79    93.5 1500.67
   103.1 1495.24   122.3 1483.36   131.9 1480.44   136.5 1480.21   141.5 1479.95
   146.5 1480.28   160.7 1481.32   170.3 1481.92   179.9 1482.42   208.8 1483.69
   218.4  1484.7     228 1486.61   237.6 1489.41   247.2 1492.62   256.8 1495.96
   266.4 1499.44     276 1503.05
#Mann= 3 , 0 , 0
       0     .06       0   136.5    .045       0   146.5     .06       0
Bank Sta=136.5,146.5
XS Rating Curve= 0 ,0
Exp/Cntr=0.3,0.1

Type RM Length L Ch R = 1 ,7208.5  ,342.9,343.4,343.8
XS GIS Cut Line= 3
     1800770.996      133009.379     1800782.501       132849.96
     1800749.631      132716.837
#Sta/Elev= 23
      10 1514.05      40  1497.8    49.9 1491.97    59.9 1485.39    69.9 1479.22
    74.9 1477.68    79.9 1476.13    84.9 1476.53    89.9 1476.92    99.9 1478.03
   109.9 1478.82   119.9 1479.28   149.8 1480.02     199 1480.48   208.8 1480.84
   218.6 1481.58   238.2 1483.62     248 1484.78   257.8 1486.27   267.6 1488.55
   277.4 1491.66   287.2 1495.01     297 1497.35
#Mann= 3 , 0 , 0
       0     .06       0    74.9    .045       0    84.9     .06       0
Bank Sta=74.9,84.9
XS Rating Curve= 0 ,0
Exp/Cntr=0.3,0.1

Type RM Length L Ch R = 1 ,6865.2  ,506.9,516.8,526.7
XS GIS Cut Line= 2
     1801090.435      133152.362     1801113.444      132881.186
#Sta/Elev= 29
    10.1 1542.53    20.2 1536.06    30.2 1529.43    40.3 1522.75    50.4 1516.12
    60.5 1509.64    70.6 1503.38    80.6 1497.35    90.7 1491.38   100.8 1485.18
   110.9 1478.48     121 1471.35     131 1467.64   136.1 1467.55   141.1 1467.47
   146.1 1468.31   151.2 1469.16   161.3 1471.24   171.4 1472.63   181.4 1473.37
   191.5 1473.98   201.6 1474.68   211.7 1475.47   221.8 1476.38   231.8 1477.33
   241.9 1478.29     252 1479.85   262.1 1482.46   272.2 1485.76
#Mann= 3 , 0 , 0
       0     .06       0   136.1    .045       0   146.1     .06       0
Bank Sta=136.1,146.1
XS Rating Curve= 0 ,0
Exp/Cntr=0.3,0.1

Type RM Length L Ch R = 1 ,6348.3  ,413.7,405.5,397.2
XS GIS Cut Line= 3
     1801504.014      133266.337     1801577.345      133151.207
     1801650.909      133036.226
#Sta/Elev= 30
     9.7 1523.68    19.5 1516.72    29.3 1509.78      39 1502.82    48.8 1495.81
    58.5 1488.69    68.3 1481.48      78 1474.46    87.8 1468.58    97.5 1464.88
   107.3 1463.14     112 1462.82     117 1462.49     122 1462.82   126.8 1463.15
   136.5 1464.74   146.3 1466.68     156 1468.34   165.8    1470   175.5 1471.62
   185.3 1473.12     195 1474.49   204.8 1475.83   214.5 1477.22   224.3 1478.62
     234 1480.05   243.8 1481.49   253.5 1482.94   263.3 1484.36     273 1485.75
#Mann= 3 , 0 , 0
       0     .06       0     112    .045       0     122     .06       0
Bank Sta=112,122
XS Rating Curve= 0 ,0
Exp/Cntr=0.3,0.1

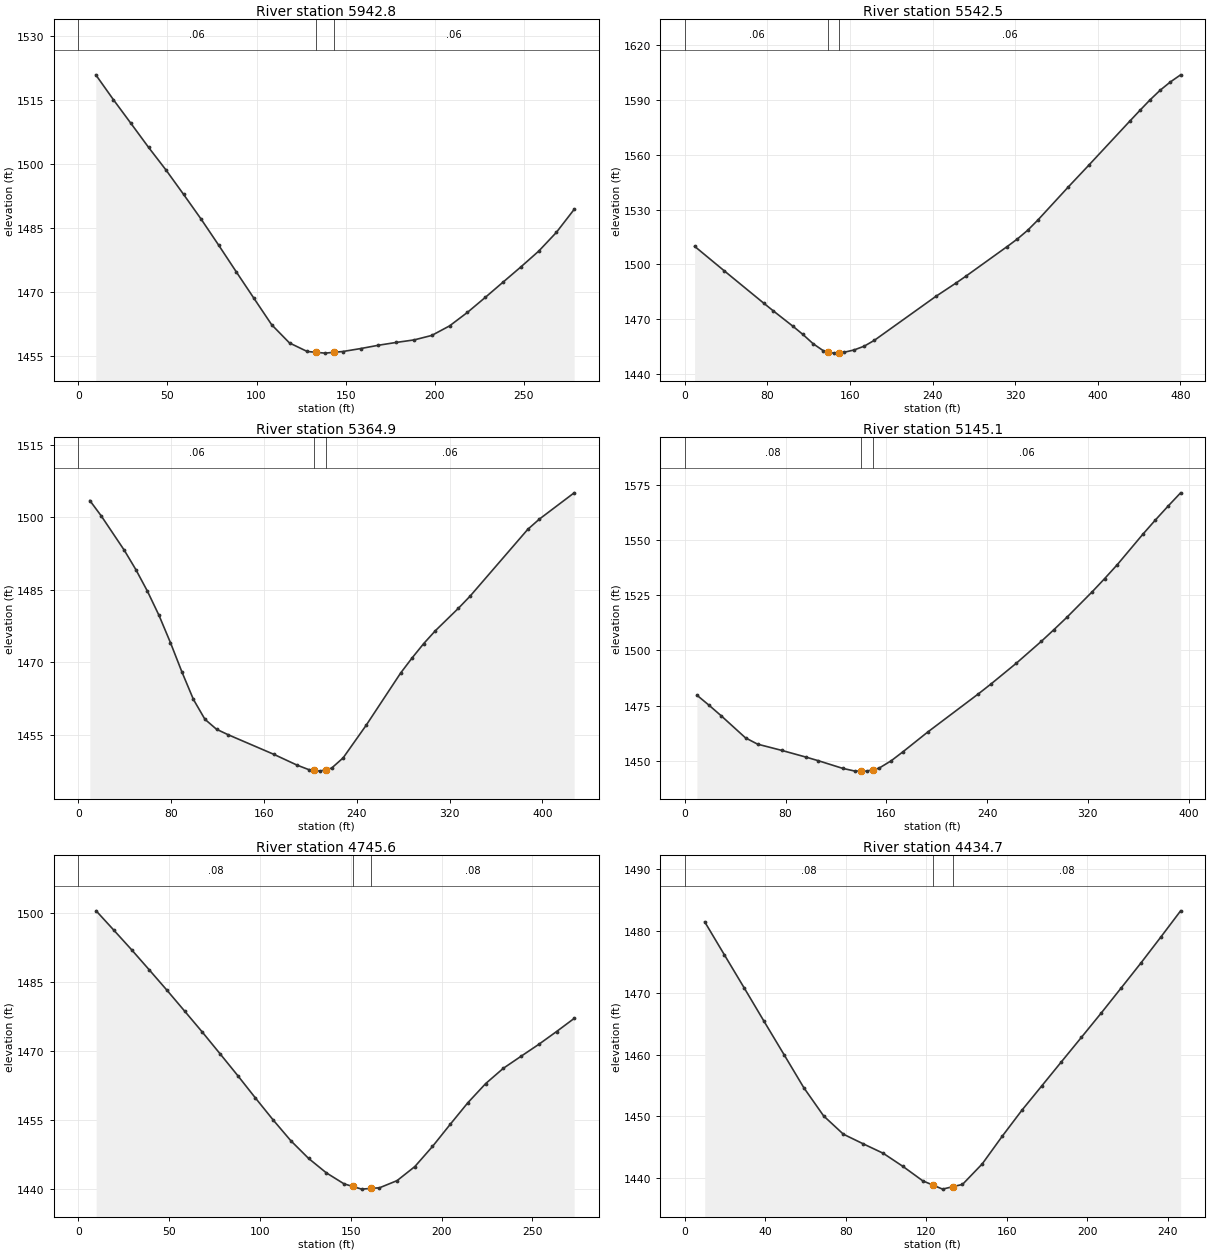
Type RM Length L Ch R = 1 ,5942.8  ,389.8,400.4,411
XS GIS Cut Line= 3
     1801887.222      133439.601     1801936.833      133354.512
     1801965.445       133177.08
#Sta/Elev= 30
     9.8 1520.95    19.7 1515.11    29.5 1509.57    39.4 1503.94    49.2 1498.62
    59.1 1492.88    68.9  1487.1    78.8 1480.96    88.6 1474.75    98.5 1468.55
   108.5 1462.32   118.5 1458.05   128.4 1456.06   133.4 1455.86   138.4 1455.67
   143.4 1455.86   148.4 1456.05   158.4 1456.74   168.4 1457.52   178.4 1458.18
   188.4 1458.77   198.3 1459.82   208.3 1462.06   218.3 1465.22   228.3 1468.73
   238.3 1472.32   248.3 1475.89   258.3 1479.59   268.2 1483.98   278.2 1489.39
#Mann= 3 , 0 , 0
       0     .06       0   133.4    .045       0   143.4     .06       0
Bank Sta=133.4,143.4
XS Rating Curve= 0 ,0
Exp/Cntr=0.3,0.1

Type RM Length L Ch R = 1 ,5542.5  ,162.6,177.6,192.6
XS GIS Cut Line= 4
     1802185.011      133603.071     1802260.601      133517.218
     1802341.824      133417.292     1802370.715      133181.945
#Sta/Elev= 30
     9.5 1509.94    38.1 1496.57    76.3 1478.87    85.8 1474.55   104.9 1466.09
   114.4 1461.67   124.3 1456.59   134.2 1452.75   139.1  1452.1   144.1 1451.44
   149.1 1451.66     154 1451.87   163.9 1453.16   173.8 1455.25   183.7 1458.48
   243.2 1482.52   262.9 1489.89   272.8 1493.78   312.3 1509.82   322.2 1513.97
   332.1  1518.7     342 1524.31   371.6 1542.51   391.4 1554.39   430.9 1578.39
   440.8 1584.34   450.6  1590.1   460.5 1595.43   470.4 1599.96   480.3 1603.85
#Mann= 3 , 0 , 0
       0     .06       0   139.1    .045       0   149.1     .06       0
Bank Sta=139.1,149.1
XS Rating Curve= 0 ,0
Exp/Cntr=0.3,0.1

Type RM Length L Ch R = 1 ,5364.9  ,205.9,219.8,233.7
XS GIS Cut Line= 3
     1802220.469      133644.532     1802494.943      133601.542
     1802626.117      133529.892
#Sta/Elev= 30
     9.9 1503.49    19.8 1500.29    39.7 1493.17    49.6 1489.19    59.5 1484.76
    69.5 1479.75    79.4 1474.09    89.3 1468.02    99.2 1462.35   109.1 1458.25
   119.1 1456.19     129 1455.07   168.7 1450.98   188.5 1448.77   198.4 1447.86
   203.4 1447.69   208.4 1447.53   213.4 1447.85   218.3 1448.16   228.2 1450.27
   248.1 1457.03   277.8 1467.83   287.8 1470.99   297.7 1473.92   307.7 1476.57
   327.6 1481.22   337.6 1483.71   387.4 1497.55   397.4 1499.66   427.3 1505.08
#Mann= 3 , 0 , 0
       0     .06       0   203.4    .045       0   213.4     .06       0
Bank Sta=203.4,213.4
XS Rating Curve= 0 ,0
Exp/Cntr=0.3,0.1

Type RM Length L Ch R = 1 ,5145.1  ,412.3,399.5,386.6
XS GIS Cut Line= 3
     1802243.997       133753.15     1802410.159      133850.847
     1802604.091      133903.438
#Sta/Elev= 30
     9.6 1479.73    19.3 1475.14    28.9 1470.39    48.2 1460.39    57.8 1457.54
    77.1  1454.7    96.4 1451.65     106 1450.05   125.3 1446.59   134.9 1445.37
   139.6 1445.35   144.6 1445.33   149.6 1446.02   154.2 1446.66   163.8 1449.98
   173.5 1454.21   192.8 1462.99   232.9 1480.22     243 1484.73   263.1 1494.12
   283.2 1504.15   293.2 1509.44   303.3 1514.93   323.4 1526.48   333.4 1532.52
   343.5 1538.87   363.6 1552.52   373.6    1559   383.6 1565.24   393.7 1571.34
#Mann= 3 , 0 , 0
       0     .08       0   139.6    .045       0   149.6     .06       0
Bank Sta=139.6,149.6
XS Rating Curve= 0 ,0
Exp/Cntr=0.3,0.1

Type RM Length L Ch R = 1 ,4745.6  ,315.1,310.9,305.9
XS GIS Cut Line= 3
     1802152.039        134222.4     1802287.727      134207.531
     1802423.415      134192.661
#Sta/Elev= 30
     9.8 1500.52    19.5 1496.33    29.3 1492.06      39 1487.69    48.8 1483.23
    58.5  1478.7    68.3  1474.1      78 1469.41    87.8 1464.63    97.5 1459.77
   107.3 1454.97     117 1450.46   126.8  1446.6   136.5 1443.48   146.3 1441.07
     151 1440.51     156 1439.92     161 1440.07   165.8 1440.21   175.5 1441.77
   185.3 1444.84     195 1449.21   204.8 1454.05   214.5 1458.75   224.3 1462.91
     234 1466.23   243.8 1468.86   253.5 1471.44   263.3 1474.23     273 1477.09
#Mann= 3 , 0 , 0
       0     .08       0     151    .045       0     161     .08       0
Bank Sta=151,161
XS Rating Curve= 0 ,0
Exp/Cntr=0.3,0.1

Type RM Length L Ch R = 1 ,4434.7  ,467.5,465.5,463.6
XS GIS Cut Line= 2
      1802283.61      134513.174      1802518.63      134439.217
#Sta/Elev= 27
     9.9 1481.43    19.7 1476.09    29.6 1470.72    39.4 1465.36    49.3    1460
    59.1 1454.67      69 1450.09    78.8 1447.14    88.7 1445.58    98.6 1444.06
   108.4 1441.94   118.3  1439.6   123.1 1438.95   128.1 1438.27   133.1 1438.66
     138 1439.03   147.8 1442.34   157.7 1446.79   167.5    1451   177.4 1454.94
   187.2 1458.85   197.1 1462.78     207 1466.73   216.8 1470.73   226.7  1474.8
   236.5 1478.95   246.4 1483.21
#Mann= 3 , 0 , 0
       0     .08       0   123.1    .045       0   133.1     .08       0
Bank Sta=123.1,133.1
XS Rating Curve= 0 ,0
Exp/Cntr=0.3,0.1

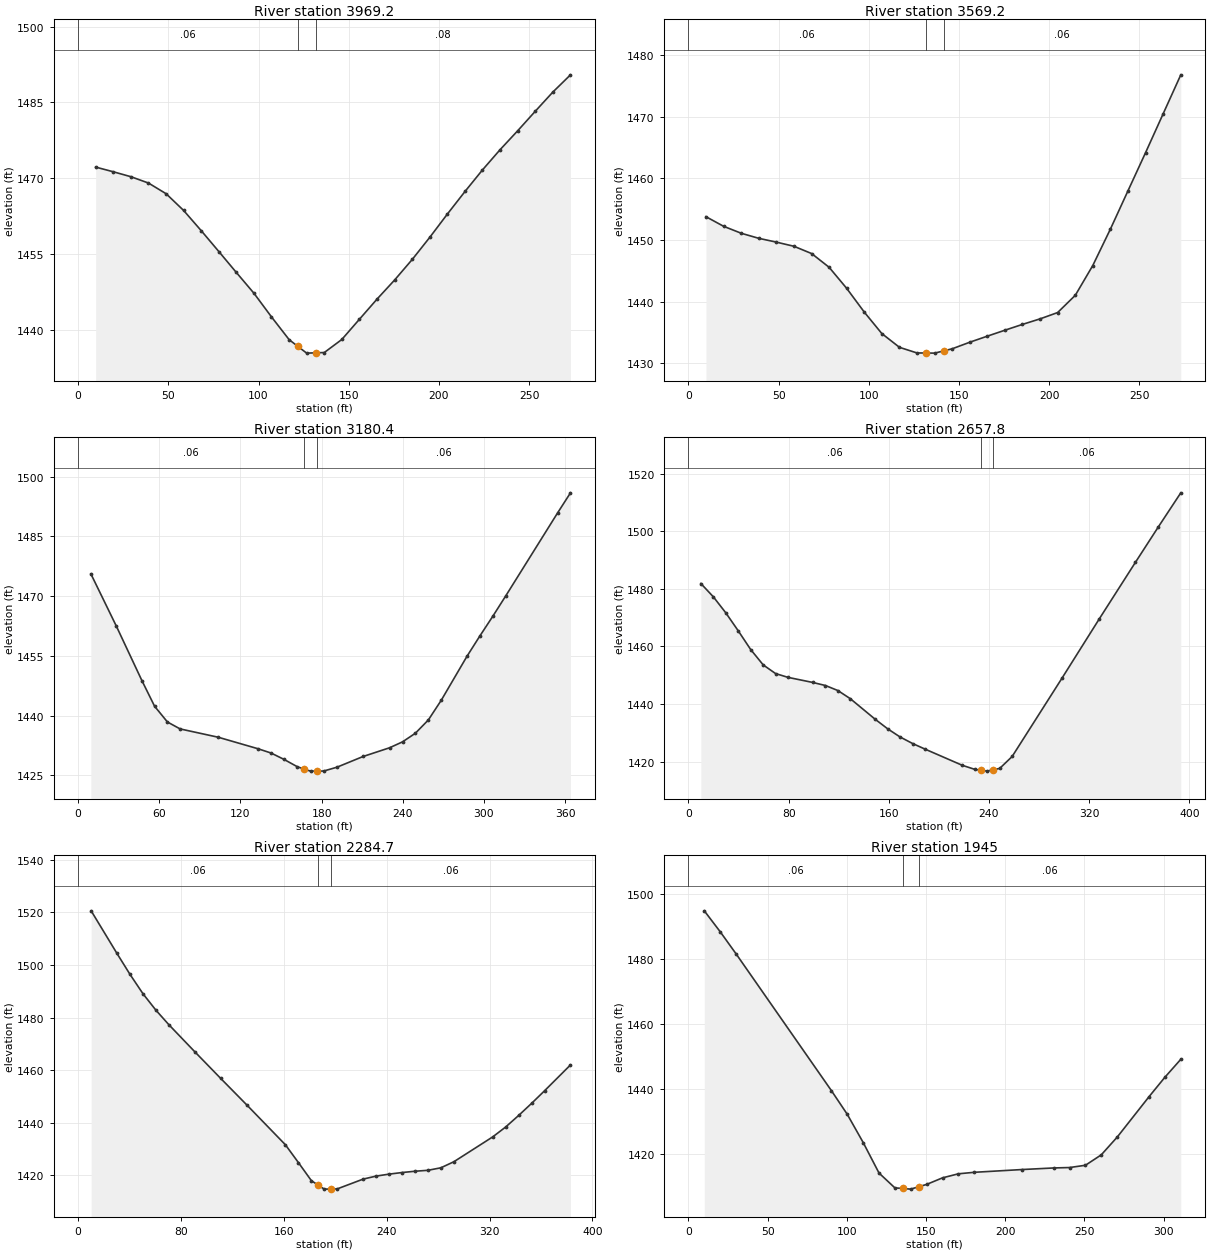
Type RM Length L Ch R = 1 ,3969.2  ,402.6,400,397.4
XS GIS Cut Line= 3
     1802437.179      134963.134     1802562.921       134910.02
     1802688.663      134856.905
#Sta/Elev= 30
     9.7 1472.21    19.5 1471.28    29.3  1470.3      39 1469.05    48.8 1466.93
    58.5 1463.62    68.3  1459.6      78  1455.5    87.7 1451.36    97.5 1447.23
   107.2 1442.56     117 1438.05   121.8 1436.73   126.7 1435.39   131.8 1435.45
   136.5 1435.51   146.2 1438.09     156 1442.11   165.8 1446.11   175.5 1449.87
   185.3 1453.95     195 1458.32   204.7  1462.9   214.5 1467.38   224.2 1471.65
     234 1475.67   243.7 1479.39   253.5 1483.27   263.2 1487.05     273 1490.47
#Mann= 3 , 0 , 0
       0     .06       0   121.8    .045       0   131.8     .08       0
Bank Sta=121.8,131.8
XS Rating Curve= 0 ,0
Exp/Cntr=0.3,0.1

Type RM Length L Ch R = 1 ,3569.2  ,378.3,388.8,399.2
XS GIS Cut Line= 3
     1802613.776      135338.925     1802731.616      135270.035
     1802849.456      135201.144
#Sta/Elev= 30
     9.7  1453.8    19.5 1452.24    29.3 1451.11      39 1450.29    48.8 1449.67
    58.5    1449    68.3 1447.82      78 1445.59    87.7 1442.19    97.5 1438.32
   107.2 1434.85     117 1432.61   126.7  1431.7   131.5 1431.69   136.5 1431.67
   141.5 1432.03   146.2 1432.37     156 1433.44   165.8 1434.43   175.5 1435.39
   185.2 1436.33     195 1437.23   204.7 1438.25   214.5 1441.05   224.2 1445.88
     234 1451.81   243.7 1457.99   253.5 1464.21   263.2 1470.48     273 1476.81
#Mann= 3 , 0 , 0
       0     .06       0   131.5    .045       0   141.5     .06       0
Bank Sta=131.5,141.5
XS Rating Curve= 0 ,0
Exp/Cntr=0.3,0.1

Type RM Length L Ch R = 1 ,3180.4  ,525.1,522.6,520
XS GIS Cut Line= 4
     1802618.883      135686.627     1802710.918      135638.966
     1802837.467      135637.323     1802955.798       135574.87
#Sta/Elev= 28
     9.4 1475.59    28.3 1462.41    47.1  1448.8    56.5 1442.34      66 1438.38
    75.4 1436.64   103.6 1434.55   132.9 1431.67   142.6 1430.59   152.3 1428.97
   162.1 1427.13   166.8  1426.6   171.8 1426.04   176.8 1426.05   181.5 1426.06
   191.3 1427.02   210.7 1429.72   230.2  1431.9   239.8 1433.39   249.3 1435.55
   258.9 1438.89   268.4 1443.81   287.5  1454.9   297.1 1460.04   306.7 1465.01
   316.2 1470.09   354.4 1490.86     364 1495.94
#Mann= 3 , 0 , 0
       0     .06       0   166.8    .045       0   176.8     .06       0
Bank Sta=166.8,176.8
XS Rating Curve= 0 ,0
Exp/Cntr=0.3,0.1

Type RM Length L Ch R = 1 ,2657.8  ,381.7,373.2,364.7
XS GIS Cut Line= 3
     1802811.171      136036.691     1803154.661      135980.813
     1803197.392      135966.021
#Sta/Elev= 29
     9.9 1481.87    19.9 1477.23    29.8  1471.7    39.8 1465.41    49.7 1458.94
    59.7  1453.6    69.6 1450.59    79.5 1449.28    99.4  1447.5   109.4 1446.45
   119.3 1444.71   129.3 1441.86   149.1 1434.74   159.1 1431.41     169 1428.58
     179 1426.31   188.9 1424.37   218.7 1418.74   228.7 1417.33   233.6 1417.03
   238.6 1416.72   243.6  1417.2   248.6 1417.67   258.5  1421.8   298.3 1448.99
   328.1 1469.59     357 1489.25   375.1 1501.42   393.2 1513.36
#Mann= 3 , 0 , 0
       0     .06       0   233.6    .045       0   243.6     .06       0
Bank Sta=233.6,243.6
XS Rating Curve= 0 ,0
Exp/Cntr=0.3,0.1

Type RM Length L Ch R = 1 ,2284.7  ,335.9,339.7,343.5
XS GIS Cut Line= 2
     1802929.503      136460.712      1803248.34      136248.702
#Sta/Elev= 30
    10.1 1520.57    30.2 1504.36    40.3 1496.43    50.4 1489.06    60.5 1482.79
    70.5 1477.31    90.7 1467.01   110.8  1456.9     131 1446.87   161.2 1431.64
   171.3 1424.88   181.4    1418   186.4 1416.39   191.4 1414.79   196.4 1414.83
   201.5 1414.88   221.7 1418.61   231.8 1419.75   241.8 1420.49   251.9  1421.1
     262 1421.59   272.1 1421.95   282.1  1422.9   292.2  1425.2   322.4 1434.64
   332.5 1438.41   342.6  1442.8   352.7 1447.41   362.7 1452.16   382.9    1462
#Mann= 3 , 0 , 0
       0     .06       0   186.4    .045       0   196.4     .06       0
Bank Sta=186.4,196.4
XS Rating Curve= 0 ,0
Exp/Cntr=0.3,0.1

Type RM Length L Ch R = 1 ,1945    ,356.1,358.5,360.9
XS GIS Cut Line= 2
     1803166.166       136680.94     1803452.133      136559.322
#Sta/Elev= 24
      10 1494.74      20 1488.32    30.1 1481.46    90.2 1439.39   100.2 1432.11
   110.3 1423.38   120.3 1413.98   130.3 1409.42   135.3 1409.23   140.3 1409.03
   145.3 1409.76   150.4 1410.49   160.4 1412.51   170.4 1413.75   180.4 1414.21
   210.5 1415.06   230.6 1415.55   240.6 1415.68   250.6 1416.38   260.6 1419.59
   270.7 1425.08   290.7 1437.47   300.7 1443.45   310.8 1449.01
#Mann= 3 , 0 , 0
       0     .06       0   135.3    .045       0   145.3     .06       0
Bank Sta=135.3,145.3
XS Rating Curve= 0 ,0
Exp/Cntr=0.3,0.1

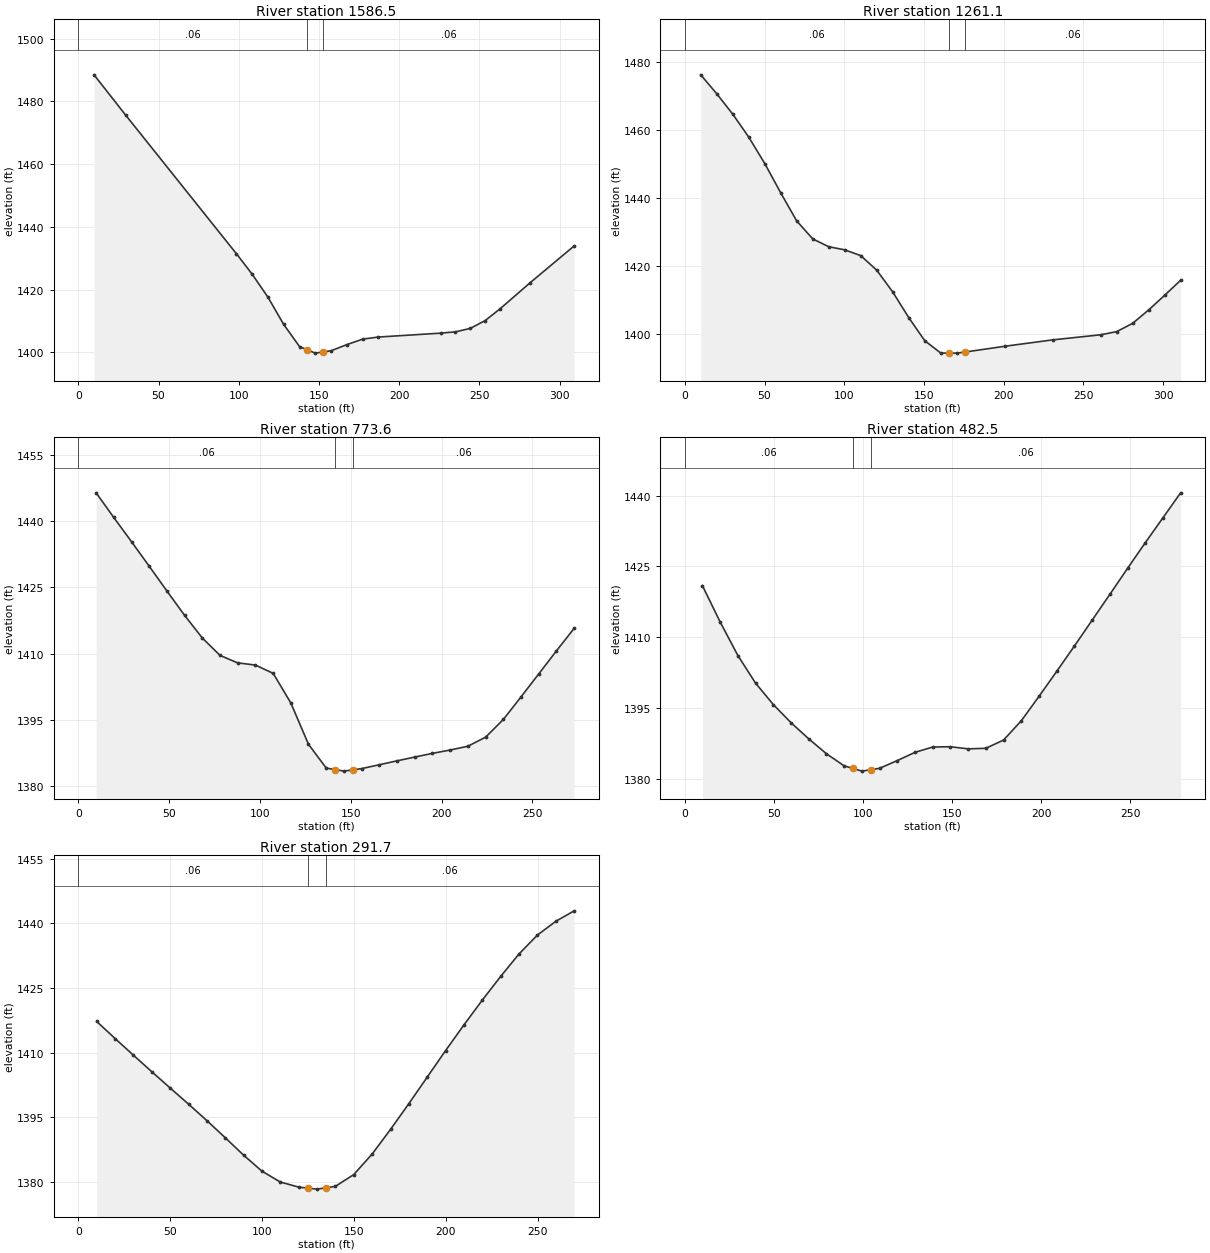
Type RM Length L Ch R = 1 ,1586.5  ,332.1,325.4,318.5
XS GIS Cut Line= 3
     1803287.498      136996.634     1803495.833      136937.109
     1803584.018      136909.552
#Sta/Elev= 21
     9.8 1488.48    29.5 1475.64    98.5 1431.49   108.3 1424.99   118.2 1417.62
     128 1408.94   137.9 1401.87   142.7 1400.84   147.7 1399.78   152.7 1400.16
   157.6 1400.54   167.4 1402.49   177.3 1404.25   187.1 1404.91   225.9 1406.15
   235.1 1406.56   244.4 1407.67   253.6 1410.15   262.9  1413.9   281.3 1422.06
   309.1 1433.95
#Mann= 3 , 0 , 0
       0     .06       0   142.7    .045       0   152.7     .06       0
Bank Sta=142.7,152.7
XS Rating Curve= 0 ,0
Exp/Cntr=0.3,0.1

Type RM Length L Ch R = 1 ,1261.1  ,495.7,487.5,479.6
XS GIS Cut Line= 2
     1803419.775      137351.575     1803674.407      137173.002
#Sta/Elev= 27
      10 1476.27    20.1 1470.66    30.1 1464.67    40.1 1457.93    50.2  1450.1
    60.2 1441.47    70.2 1433.22    80.3 1427.92    90.3 1425.63   100.3 1424.71
   110.4    1423   120.4 1418.71   130.4 1412.32   140.5 1404.72   150.5 1397.95
   160.5 1394.31   165.6 1394.29   170.6 1394.28   175.6 1394.59   200.7  1396.3
   230.7 1398.18   260.8 1399.68   270.9 1400.61   280.9 1403.05   290.9 1406.98
     301 1411.33     311 1415.75
#Mann= 3 , 0 , 0
       0     .06       0   165.6    .045       0   175.6     .06       0
Bank Sta=165.6,175.6
XS Rating Curve= 0 ,0
Exp/Cntr=0.3,0.1

Type RM Length L Ch R = 1 ,773.6   ,296.1,291.1,287.4
XS GIS Cut Line= 3
     1803809.758      137729.431     1803881.675      137613.413
     1803953.593      137497.396
#Sta/Elev= 30
     9.8 1446.38    19.5 1440.81    29.3 1435.32      39 1429.79    48.7 1424.22
    58.5 1418.67    68.3 1413.53      78 1409.61    87.7 1407.92    97.5 1407.42
   107.3 1405.54     117 1398.85   126.7 1389.51   136.5 1384.12   141.2 1383.79
   146.3 1383.43   151.2 1383.72     156    1384   165.7 1384.87   175.5 1385.76
   185.2 1386.61     195 1387.45   204.8 1388.21   214.5 1389.06   224.3 1391.13
     234 1395.11   243.7  1400.2   253.5 1405.42   263.2  1410.6     273 1415.74
#Mann= 3 , 0 , 0
       0     .06       0   141.2    .045       0   151.2     .06       0
Bank Sta=141.2,151.2
XS Rating Curve= 0 ,0
Exp/Cntr=0.3,0.1

Type RM Length L Ch R = 1 ,482.5   ,189.3,190.9,190.9
XS GIS Cut Line= 2
     1804114.225      137833.281     1804196.898      137567.626
#Sta/Elev= 30
     9.9 1420.93    19.9 1413.21    29.8 1406.15    39.7 1400.32    49.7 1395.77
    59.6 1391.95    69.6 1388.51    79.5 1385.37    89.4 1382.82    94.4 1382.26
    99.4  1381.7   104.4    1382   109.3  1382.3   119.2 1383.93   129.2 1385.68
   139.1  1386.8     149 1386.86     159 1386.41   168.9 1386.53   178.9 1388.29
   188.8 1392.35   198.7  1397.5   208.7 1402.82   218.6 1408.17   228.5 1413.61
   238.5  1419.1   248.4 1424.59   258.3 1429.99   268.3 1435.31   278.2 1440.58
#Mann= 3 , 0 , 0
       0     .06       0    94.4    .045       0   104.4     .06       0
Bank Sta=94.4,104.4
XS Rating Curve= 0 ,0
Exp/Cntr=0.3,0.1

Type RM Length L Ch R = 1 ,291.7   ,300.2,291.7,283.2
XS GIS Cut Line= 2
     1804262.465      137881.627      1804360.57      137630.302
#Sta/Elev= 29
      10 1417.25      20 1413.29      30 1409.41      40 1405.57      50 1401.79
      60 1398.05    69.9 1394.25    79.9 1390.27    89.9 1386.22    99.9  1382.5
   109.9 1379.97   119.9 1378.79   124.9 1378.55   129.9 1378.32   134.9 1378.64
   139.9 1378.97   149.9 1381.71   159.9 1386.48   169.9  1392.2   179.9  1398.2
   189.9 1404.36   199.8 1410.47   209.8 1416.43   219.8  1422.2   229.8  1427.7
   239.8 1432.93   249.8 1437.31   259.8  1440.5   269.8 1442.94
#Mann= 3 , 0 , 0
       0     .06       0   124.9    .045       0   134.9     .06       0
Bank Sta=124.9,134.9
XS Rating Curve= 0 ,0
Exp/Cntr=0.3,0.1

Chan Stop Cuts=-1
Use User Specified Reach Order=0